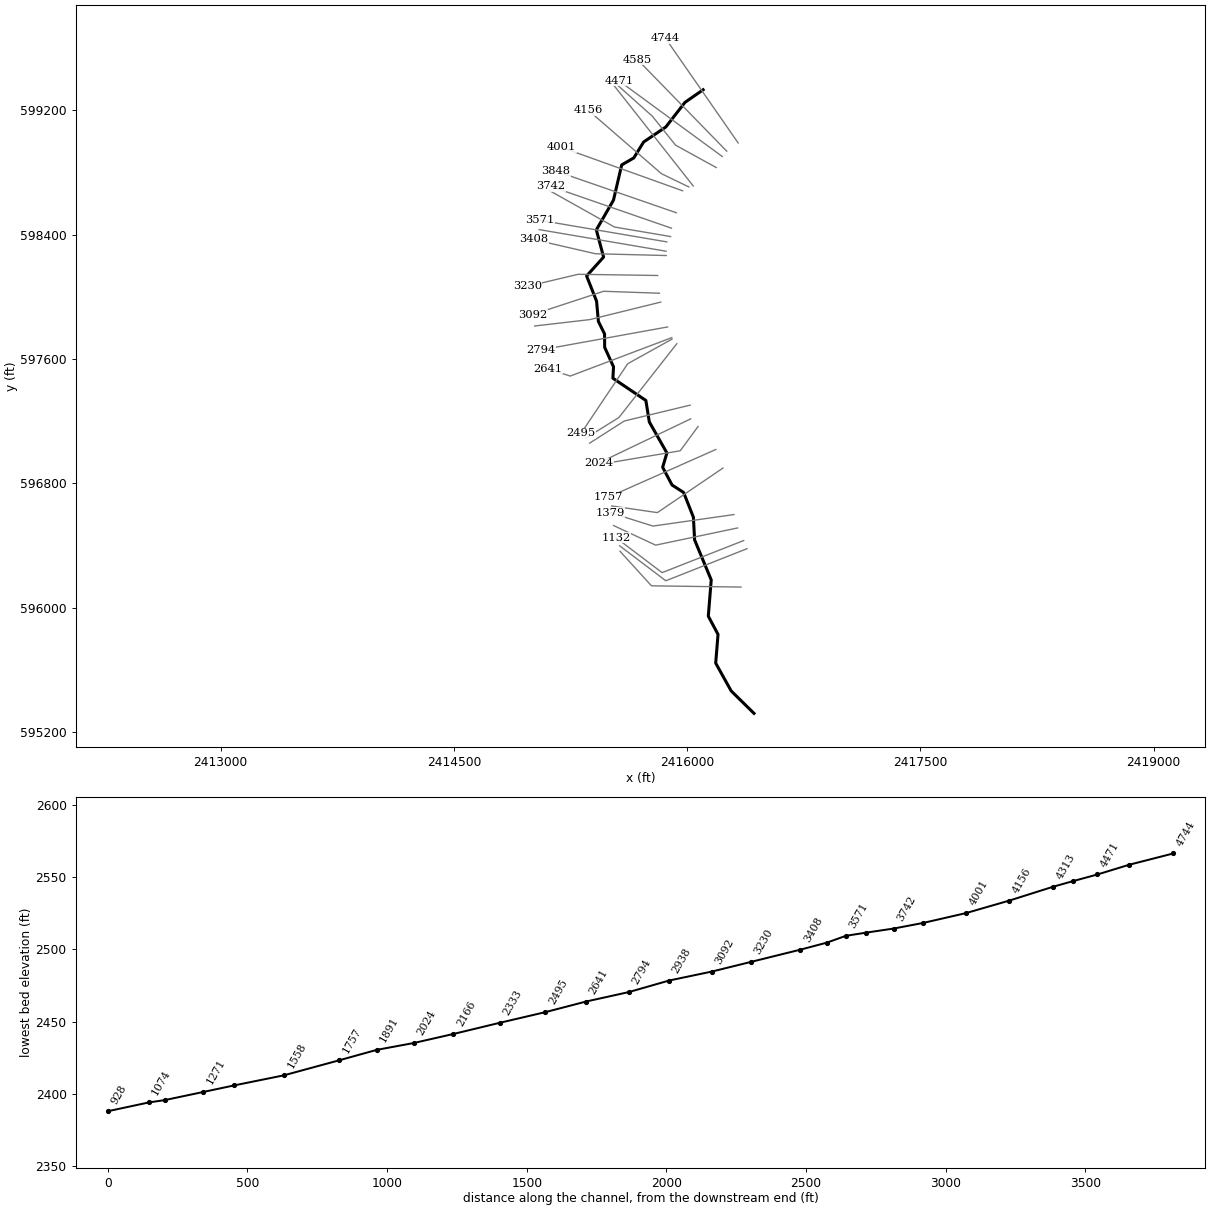
--- GRAVLCKRN.prj (project) ---

Proj Title=GRAVLCKRN
Current Plan=p01
Default Exp/Contr=0,0
English Units
Geom File=g01
Flow File=f01
Plan File=p01
BEGIN DESCRIPTION:
Stream Name: Gravel Lick Run
Flood Zone: Approximate
Pendleton County, West Virginia
HEC-RAS Version: 5.0.7
Hydrology Method:
Regression
END DESCRIPTION:
DSS File=dss
DSS Export Rating Curves= 0
DSS Export Rating Curve Sorted= 0
DSS Export Volume Flow Curves= 0
DXF OffsetX= 0
DXF OffsetY= 0
DXF ScaleX= 0
DXF ScaleY= 0

--- GRAVLCKRN.p01 (plan) ---

Plan Title=Floodplain
Program Version=5.07
Short Identifier=Floodplain
Geom File=g01
Flow File=f01
Subcritical Flow
K Sum by GR= 0
Std Step Tol= 0.01
Critical Tol= 0.01
Num of Std Step Trials= 20
Max Error Tol= 0.3
Flow Tol Ratio= 0.001
Split Flow NTrial= 30
Split Flow Tol= 0.02
Split Flow Ratio= 0.02
Log Output Level= 0
Friction Slope Method= 1
Unsteady Friction Slope Method= 2
Unsteady Bridges Friction Slope Method= 1
Parabolic Critical Depth
Global Vel Dist= 0 , 0 , 0
Global Log Level= 0
CheckData=True
Encroach Param=-1 ,0,0, 0
Computation Interval=0.1SEC
Output Interval=1MIN
Instantaneous Interval=Max Profile
Mapping Interval=1HOUR
Computation Time Step Use Courant=        0
Computation Time Step Use Time Series=    0
Computation Time Step Count To Double=0
Computation Time Step Max Doubling=0
Computation Time Step Max Halving=0
Computation Time Step Residence Courant=0
Run HTab= 0
Run UNet= 0
Run Sediment= 0
Run PostProcess= 0
Run WQNet= 0
Run RASMapper= 0
UNET Theta= 0
UNET Theta Warmup= 0
UNET ZTol= 0
UNET ZSATol= 0
UNET MxIter= 0
UNET Max Iter WO Improvement= 0
UNET MaxInSteps= 0
UNET DtIC= 0
UNET DtMin= 0
UNET MaxCRTS= 0
UNET WFStab= 0
UNET SFStab= 0
UNET WFX= 1
UNET SFX= 1
UNET 1D Methodology=Finite Difference
UNET DSS MLevel= 1
UNET Pardiso=0
UNET DZMax Abort= 0
UNET Use Existing IB Tables= 0
UNET Froude Reduction=False
UNET Froude Limit= 0
UNET Froude Power= 0
UNET D1 Cores= 0
UNET D2 Coriolis=0
UNET D2 Cores= 0
UNET D2 Theta= 1
UNET D2 Theta Warmup= 1
UNET D2 Z Tol= 0.01
UNET D2 Volume Tol= 0.01
UNET D2 Max Iterations= 20
UNET D2 Equation= 0
UNET D2 RampUpFraction=0.1
UNET D2 TimeSlices= 1
UNET D2 BCVolumeCheck=0
UNET D1D2 MaxIter= 0
UNET D1D2 ZTol=0.01
UNET D1D2 QTol=0.1
UNET D1D2 MinQTol=1
DSS File=dss
Write IC File= 0
Write IC File at Fixed DateTime=0
Write IC File at Sim End=0
Echo Input=False
Echo Parameters=False
Echo Output=False
Write Detailed= 0
HDF Write Warmup=0
HDF Write Time Slices=0
HDF Flush=0
HDF Face Node Velocities=0
HDF Compression= 1
HDF Chunk Size= 1
HDF Spatial Parts= 1
HDF Use Max Rows=0
HDF Fixed Rows= 1
Calibration Method= 0
Calibration Iterations= 20
Calibration Max Change=0.05
Calibration Tolerance=0.2
Calibration Maximum=1.5
Calibration Minimum=0.5
Calibration Optimization Method= 1
WQ AD Non Conservative
WQ ULTIMATE=-1
WQ Max Comp Step=1HOUR
WQ Output Interval=15MIN
WQ Output Selected Increments= 0
WQ Output face flow=0
WQ Output face velocity=0
WQ Output face area=0
WQ Output face dispersion=0
WQ Output cell volume=0
WQ Output cell surface area=0
WQ Output cell continuity=0
WQ Output cumulative cell continuity=0
WQ Output face conc=0
WQ Output face dconc_dx=0
WQ Output face courant=0
WQ Output face peclet=0
WQ Output face adv mass=0
WQ Output face disp mass=0
WQ Output cell mass=0
WQ Output cell source sink temp=0
WQ Output nsm pathways=0
WQ Output nsm derived pathways=0
WQ Output MaxMinRange=-1
WQ Daily Max Min Mean=-1
WQ Daily Range=0
WQ Daily Time=0
WQ Create Restart=0
WQ Fixed Restart=0
WQ System Summary=0
WQ Write To DSS=0
WQ Use Fixed Temperature=0
Sorting and Armoring Iterations= 10
XS Update Threshold= 0.02
Bed Roughness Predictor= 0
Hydraulics Update Threshold= 0.02
Energy Slope Method= 1
Volume Change Method= 1
Sediment Retention Method= 0
XS Weighting Method= 0
Number of US Weighted Cross Sections= 1
Number of DS Weighted Cross Sections= 1
Upstream XS Weight=0
Main XS Weight=1
Downstream XS Weight=0
Number of DS XS's Weighted with US Boundary= 1
Upstream Boundary Weight= 1
Weight of XSs Associated with US Boundary= 0
Number of US XS's Weighted with DS Boundary= 1
Downstream Boundary Weight= 0.5
Weight of XSs Associated with DS Boundary= 0.5
Percentile Method= 0
Sediment Output Level= 3
Mass or Volume Output= 0
Output Increment Type= 1
Profile and TS Output Increment= 1
XS Output Flag= 0
XS Output Increment= 10
Write Gradation File= 0
Read Gradation Hotstart= 0
Write HDF5 File= 1
Write Binary Output= 1
Write DSS Sediment File= 0
SV Curve= 0
Specific Gage Flag= 0

--- GRAVLCKRN.f01 (steady flow) ---

Flow Title=Flows
Program Version=5.07
Number of Profiles= 6
Profile Names=P100yr,P10yr,P25yr,P50yr,P500yr,P101yr
River Rch & RM=GRAVLCKRN,Main            ,4744
     555     260     367     458     813     675
River Rch & RM=GRAVLCKRN,Main            ,4156
     622     291     411     513     913     757
River Rch & RM=GRAVLCKRN,Main            ,2333
     971     451     639     800    1431    1182
Boundary for River Rch & Prof#=GRAVLCKRN,Main            , 1
Up Type= 0
Dn Type= 3
Dn Slope=0.01638
Boundary for River Rch & Prof#=GRAVLCKRN,Main            , 2
Up Type= 0
Dn Type= 3
Dn Slope=0.01638
Boundary for River Rch & Prof#=GRAVLCKRN,Main            , 3
Up Type= 0
Dn Type= 3
Dn Slope=0.01638
Boundary for River Rch & Prof#=GRAVLCKRN,Main            , 4
Up Type= 0
Dn Type= 3
Dn Slope=0.01638
Boundary for River Rch & Prof#=GRAVLCKRN,Main            , 5
Up Type= 0
Dn Type= 3
Dn Slope=0.01638
Boundary for River Rch & Prof#=GRAVLCKRN,Main            , 6
Up Type= 0
Dn Type= 3
Dn Slope=0.01638
DSS Import GetInterval= 0
DSS Import GetPeak= 0
DSS Import FillOption= 0

--- GRAVLCKRN.g01 (geometry) ---

Geom Title=Geometry
Program Version=5.07

River Reach=GRAVLCKRN       ,Main
Reach XY= 30
     2416102.922      599331.303     2415986.176       599250.25
      2415863.04       599092.01     2415720.387      598995.491
     2415657.112       598893.08     2415579.368      598848.073
     2415526.432      598621.524     2415416.326      598430.508
     2415462.903      598255.568      2415353.76      598134.114
     2415417.773      597972.039     2415429.489      597841.757
     2415469.276      597761.099     2415469.822      597675.098
     2415526.814      597550.033     2415522.833      597476.635
     2415734.783      597333.557     2415756.966      597195.477
     2415870.029       596996.14     2415842.686      596904.045
     2415903.298      596789.831     2415977.619      596742.033
     2416040.353      596582.986     2416048.153      596437.095
     2416154.971      596179.841     2416136.239       595946.72
     2416198.681      595829.662     2416183.726      595644.959
     2416283.263      595466.018     2416430.011      595321.767

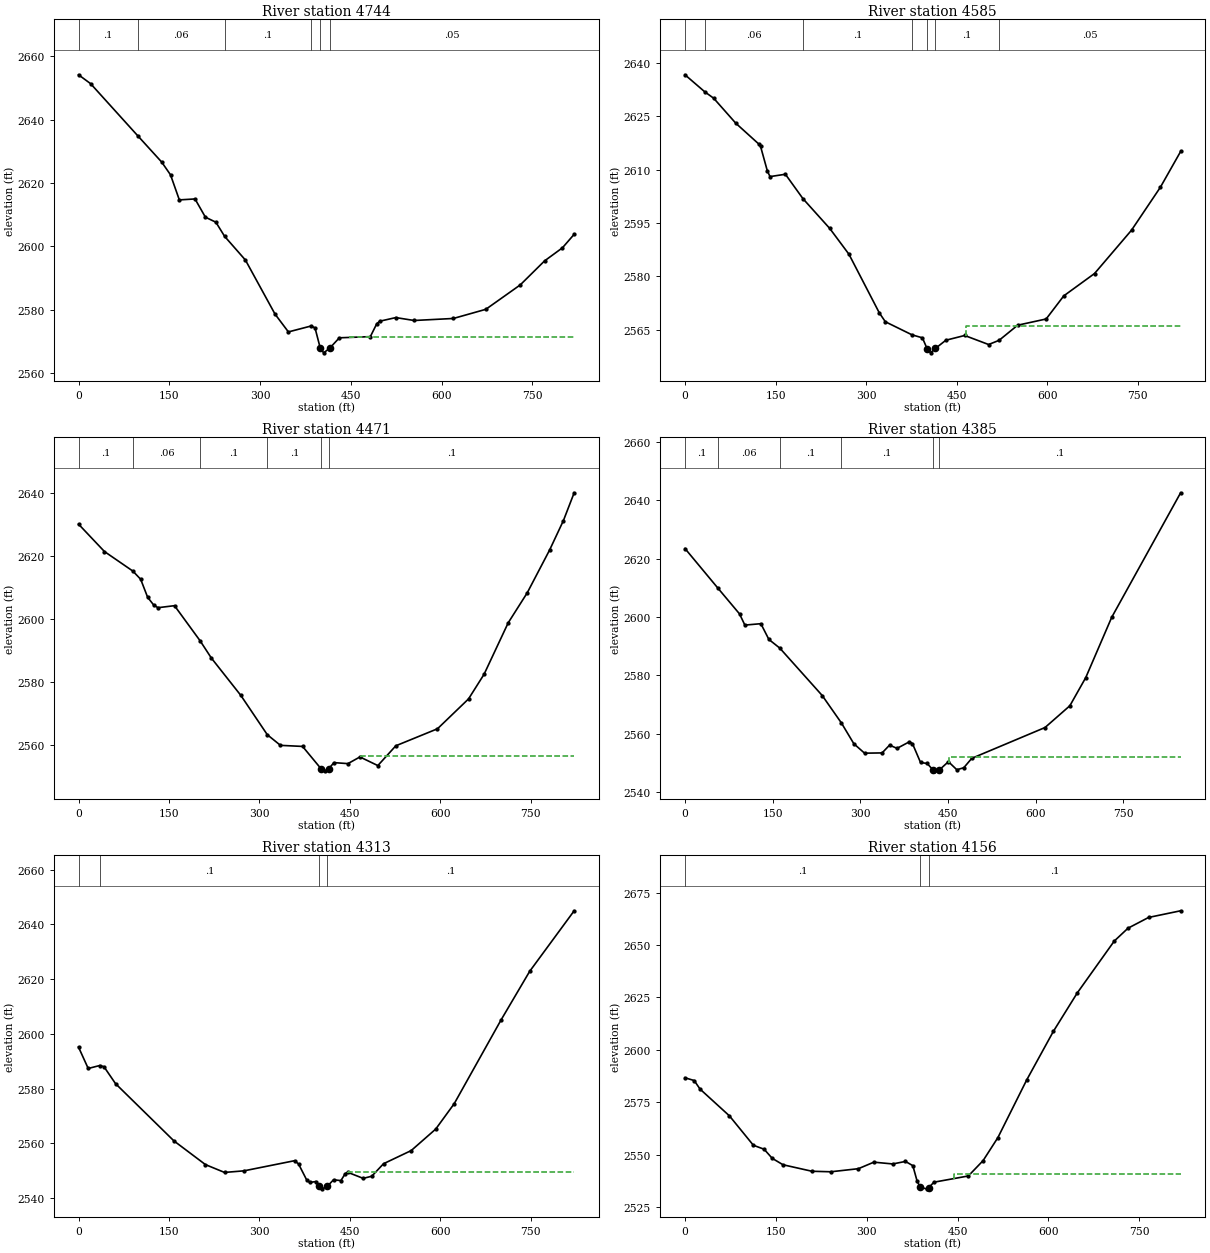
Type RM Length L Ch R = 1 ,4744    ,156.4,158.8,159.9
XS GIS Cut Line= 2
     2416328.247      598989.223     2415861.169      599661.978
#Sta/Elev= 30
       0 2654.19      20 2651.38   98.352634.821   137.4 2626.62     152 2622.59
   166.6 2614.66   192.5 2614.96   209.7 2609.19     227 2607.61  241.382603.151
   275.8 2595.65   324.7 2578.58   346.8 2572.95   384.42574.825   390.8 2574.22
   399.4 2567.87   405.1 2566.34   414.9 2567.78     431 2571.09   482.2 2571.46
   492.8 2575.52   497.7 2576.33   524.3 2577.48   554.6 2576.56   619.4  2577.2
     673 2580.09   729.9  2587.8   770.1 2595.39   799.6 2599.52     819 2603.79
#Mann= 6 ,-1 , 0
       0      .1       0   98.35     .06       0  241.38      .1       0
   384.4     .05       0   399.4    .045       0   414.9     .05       0
#XS Ineff= 2 , 0
                          447.66         2571.43
Permanent Ineff=
       F       F
Bank Sta=399.4,414.9
XS Rating Curve= 0 ,0
Exp/Cntr=0.3,0.1

Type RM Length L Ch R = 1 ,4585    ,111.2,113.5,114.9
XS GIS Cut Line= 2
     2416254.711      598936.452     2415681.883      599524.247
#Sta/Elev= 30
       0 2636.66   32.932631.848    47.5 2630.07    84.2 2623.03   122.5 2617.15
   125.2  2616.5   136.3 2609.69   140.8 2608.03   166.3 2608.69  195.342601.832
   239.8 2593.44   271.5 2586.21   321.8 2569.72   331.8 2567.22  375.972563.541
   393.2  2562.7     401 2559.62   406.7 2558.48   414.7 2559.72   432.1 2562.03
   463.2 2563.36   502.8 2560.82  520.162561.998   550.9 2566.25   598.1    2568
   627.3  2574.5   678.2 2580.78   739.5 2592.97   787.2 2605.02   820.8 2615.09
#Mann= 7 ,-1 , 0
       0      .1       0   32.93     .06       0  195.34      .1       0
  375.97      .1       0     401    .045       0   414.7      .1       0
  520.16     .05       0
#XS Ineff= 2 , 0
                          465.66         2566.04
Permanent Ineff=
       F       F
Bank Sta=401,414.7
XS Rating Curve= 0 ,0
Exp/Cntr=0.3,0.1

Type RM Length L Ch R = 1 ,4471    ,88.5,86,83
XS GIS Cut Line= 2
     2416225.665      598902.396     2415562.678       599388.33
#Sta/Elev= 30
       0 2630.08      43 2621.38    90.12615.177   103.1 2612.57   114.6 2606.87
   124.5 2604.44   131.7 2603.55   159.2 2604.19  201.592593.061   220.4 2587.54
   269.1 2575.73  313.092563.229   334.9 2559.85   371.6 2559.51   402.72552.309
   409.3 2551.76     415 2552.43   423.6 2554.37   446.8 2554.05   466.7 2556.17
   496.4 2553.43   526.2 2559.71   595.3 2565.11   646.8 2574.59   672.6 2582.42
   712.6 2598.75   744.1 2608.25   781.3 2621.87   804.2 2631.22     822 2640.03
#Mann= 6 ,-1 , 0
       0      .1       0    90.1     .06       0  201.59      .1       0
  313.09      .1       0   402.7    .045       0     415      .1       0
#XS Ineff= 2 , 0
                          468.17         2556.56
Permanent Ineff=
       F       F
Bank Sta=402.7,415
XS Rating Curve= 0 ,0
Exp/Cntr=0.3,0.1

Type RM Length L Ch R = 1 ,4385    ,72.4,72.2,72.1
XS GIS Cut Line= 4
2416187.08311406  598831.25357422415925.65554361598975.070064781
2415776.54901478599161.1346221282415544.13856254599368.609318211
#Sta/Elev= 30
       0 2623.51   56.862609.798    93.4 2601.07   102.5 2597.24   129.9 2597.72
   143.6 2592.32  162.292589.344   234.9 2573.08  267.722563.678   289.1 2556.52
   307.4  2553.3   337.4 2553.39   350.2 2556.06     363 2554.95   384.3 2557.23
   389.4 2556.58   403.2 2550.11   414.6 2549.76  424.53 2547.55   426.9 2547.24
   435.5 2547.57   450.9 2550.38   465.3 2547.62   477.2  2548.3   490.9 2551.53
   616.3  2562.1   658.8 2569.57     686 2579.23   730.4  2599.9   848.4 2642.63
#Mann= 6 ,-1 , 0
       0      .1       0   56.86     .06       0  162.29      .1       0
  267.72      .1       0  424.53    .045       0   435.5      .1       0
#XS Ineff= 2 , 0
                          452.49         2551.85
Permanent Ineff=
       F       F
Bank Sta=424.53,435.5
XS Rating Curve= 0 ,0
Exp/Cntr=0.3,0.1

Type RM Length L Ch R = 1 ,4313    ,153.7,157.2,158.6
XS GIS Cut Line= 2
     2416039.251      598712.733      2415530.12      599358.414
#Sta/Elev= 30
       0 2595.14    16.1 2587.32   35.182588.405    42.3 2587.95    61.4 2581.78
   158.3 2560.84   210.6 2552.17   242.2 2549.31   274.5 2549.89   358.4  2553.6
     365 2552.42   378.7 2546.49     384 2545.65     394 2545.99   399.1 2544.27
     404 2543.31   412.5 2544.18   423.1 2546.62   435.3 2546.32   442.5 2548.87
   446.7 2549.35   472.3 2547.14   486.5 2547.92     506 2552.49   551.9  2557.3
   592.6 2565.16   623.3 2574.45   700.8 2604.99   748.5 2622.85   822.3 2644.99
#Mann= 4 ,-1 , 0
       0     .06       0   35.18      .1       0   399.1    .045       0
   412.5      .1       0
#XS Ineff= 2 , 0
                          447.73         2549.52
Permanent Ineff=
       F       F
Bank Sta=399.1,412.5
XS Rating Curve= 0 ,0
Exp/Cntr(USF)=0,0
Exp/Cntr=0.3,0.1

Type RM Length L Ch R = 1 ,4156    ,151.6,155.1,159
XS GIS Cut Line= 3
 2416010.9280512598706.5515910542415835.17209449598791.554336988
     2415364.426      599199.798
#Sta/Elev= 30
       0 2586.68    15.2 2585.37    24.9 2581.28    73.4 2568.51   112.9  2554.5
   130.7 2552.59     144 2548.27   161.8  2545.2   209.7 2542.09   240.9 2541.85
   286.3 2543.32   311.8 2546.43     343 2545.58     364 2546.78   376.2 2544.76
     383 2537.65   388.3 2534.42   398.9 2533.71   402.5 2534.31     411 2536.88
   467.8 2539.85   492.2 2547.18   516.6 2558.15   564.1 2585.61   608.1 2608.77
   647.7 2627.17   708.7 2651.88   731.4 2658.02   765.4 2663.15   818.3 2666.33
#Mann= 3 ,-1 , 0
       0      .1       0   388.3    .045       0   402.5      .1       0
#XS Ineff= 2 , 0
                          443.77         2540.83
Permanent Ineff=
       F       F
Bank Sta=388.3,402.5
XS Rating Curve= 0 ,0
Exp/Cntr=0.3,0.1

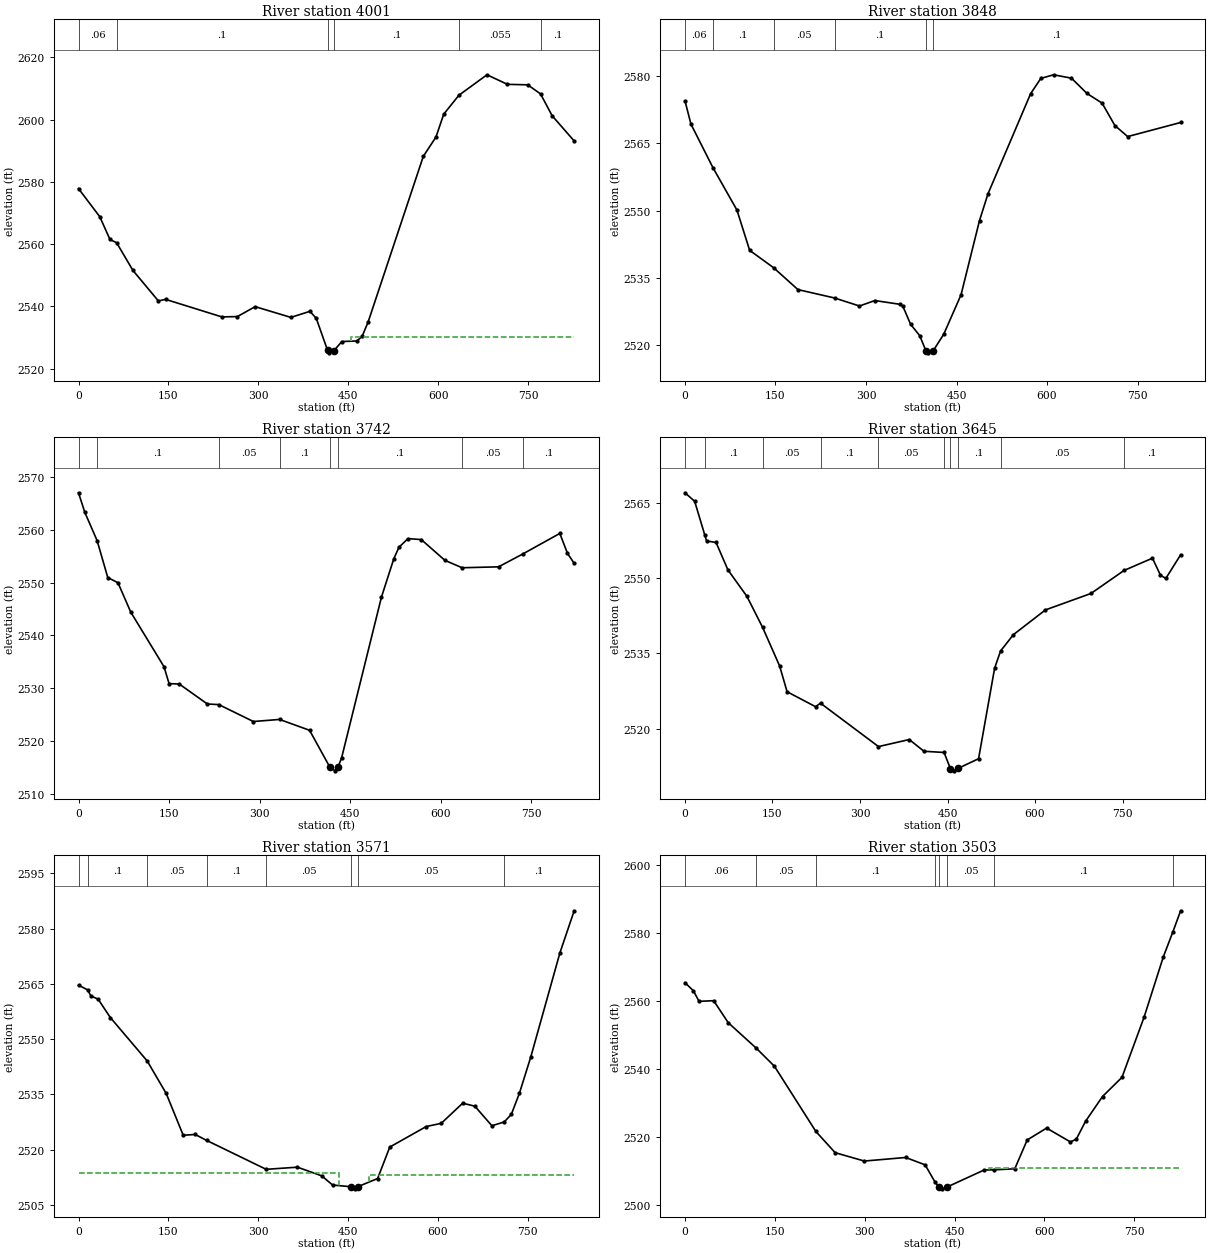
Type RM Length L Ch R = 1 ,4001    ,153.5,152.9,153.6
XS GIS Cut Line= 2
2415970.70080687598681.9736422522415192.44280687598960.834642252
#Sta/Elev= 30
       0 2577.84    35.5 2568.79    52.5 2561.48   63.56 2560.44    90.8 2551.53
   133.2 2541.74   145.1 2542.25     239 2536.61   264.9 2536.71   294.7  2539.9
   354.2 2536.45     386  2538.4   396.6 2536.12   415.4 2525.85   417.9 2525.06
   426.4 2525.81   439.1 2528.69   464.6 2528.88   473.1 2530.39   482.9 2534.89
   575.1 2588.21   596.3 2594.44   609.1 2601.75  634.532607.845   681.3 2614.41
   715.3 2611.34   749.3 2611.18  770.632608.258     790 2601.24   826.7 2593.14
#Mann= 6 ,-1 , 0
       0     .06       0   63.56      .1       0   415.4    .045       0
   426.4      .1       0  634.53    .055       0  770.63      .1       0
#XS Ineff= 2 , 0
                           454.6         2530.07
Permanent Ineff=
       F       F
Bank Sta=415.4,426.4
XS Rating Curve= 0 ,0
Exp/Cntr=0.3,0.1

Type RM Length L Ch R = 1 ,3848    ,105.7,105.6,106.2
XS GIS Cut Line= 2
     2415930.589      598540.501     2415154.382      598809.159
#Sta/Elev= 30
       0 2574.46     9.9 2569.27   46.232559.586    86.1 2550.11   107.2 2541.12
  147.04 2537.23   187.2 2532.37  247.862530.502   289.2 2528.71   314.6 2529.93
   356.9 2529.08   361.2 2528.62   373.9 2524.64   389.1 2522.08   399.2 2518.74
   403.5 2518.27   411.1 2518.67   428.9 2522.44   457.5 2531.22   488.1 2547.77
   502.2 2553.75   572.8 2576.05   589.7 2579.46   610.9 2580.27   640.5 2579.51
   666.2 2576.11   691.3 2573.94   712.4 2568.96   733.6 2566.49   821.4 2569.63
#Mann= 6 ,-1 , 0
       0     .06       0   46.23      .1       0  147.04     .05       0
  247.86      .1       0   399.2    .045       0   411.1      .1       0
Bank Sta=399.2,411.1
XS Rating Curve= 0 ,0
Exp/Cntr(USF)=0,0
Exp/Cntr=0.3,0.1

Type RM Length L Ch R = 1 ,3742    ,100,97.8,95.6
XS GIS Cut Line= 2
2415899.12196849598441.3798507292415122.91496849598710.037850729
#Sta/Elev= 30
       0 2566.99    10.4  2563.3   30.812557.943    48.5 2550.96    65.4 2549.97
    86.6 2544.41   141.6  2534.1   150.1 2530.89     167 2530.81   213.6 2527.03
  232.432526.924   289.8 2523.72  333.252524.113   382.9 2522.06   416.12515.178
   425.2 2514.39   430.3 2515.18     436 2516.84     502 2547.24   522.5  2554.5
     531 2556.68     546 2558.32     568 2558.14   607.2 2554.21  635.692552.808
   696.1 2552.98   736.52555.428   797.6  2559.3   810.3 2555.54   821.4 2553.64
#Mann= 8 ,-1 , 0
       0     .06       0   30.81      .1       0  232.43     .05       0
  333.25      .1       0   416.1    .045       0   430.3      .1       0
  635.69     .05       0   736.5      .1       0
Bank Sta=416.1,430.3
XS Rating Curve= 0 ,0
Exp/Cntr=0.3,0.1

Type RM Length L Ch R = 1 ,3645    ,69.9,73.6,77.4
XS GIS Cut Line= 3
 2415893.7951742598387.5648528862415533.13579249 598448.73676215
2415111.18143746598685.219846406
#Sta/Elev= 30
       0 2567.01    16.6 2565.31   33.712558.678      37 2557.41    53.3  2557.1
    73.6 2551.64     106 2546.39  133.032540.183   162.3 2532.46     175 2527.35
   223.7 2524.37  232.352525.062  331.672516.414   384.4 2517.82   409.6 2515.48
  444.052515.244   454.9 2512.02   460.7 2511.58  467.83 2512.05   503.2    2514
   530.7 2532.05  540.922535.472   562.8 2538.72   617.8 2543.66   695.9 2546.94
  752.382551.518   801.2 2553.97   814.9 2550.59   824.1 2549.93   849.5 2554.65
#Mann= 10 ,-1 , 0
       0     .06       0   33.71      .1       0  133.03     .05       0
  232.35      .1       0  331.67     .05       0  444.05      .1       0
   454.9    .045       0  467.83      .1       0  540.92     .05       0
  752.38      .1       0
Bank Sta=454.9,467.83
XS Rating Curve= 0 ,0
Exp/Cntr=0.5,0.3

Type RM Length L Ch R = 1 ,3571    ,70.5,68.3,69.3
XS GIS Cut Line= 2
2415869.58129345598353.1556539242415053.95583659598492.066864546
#Sta/Elev= 30
       0 2564.65   15.31 2563.35    20.6 2561.74    32.8 2560.83    53.1 2555.86
  114.632544.071   146.4 2535.24   174.8 2523.89   194.8 2524.11  213.95 2522.49
  313.272514.647   365.5 2515.23     406 2512.88   424.1 2510.39   454.7 2509.92
   462.2 2509.35   466.9 2509.98   499.3 2512.15   519.6 2520.69   580.5 2526.27
   605.5 2527.13   641.3  2532.6   661.6 2531.79     690 2526.48  710.562527.501
   722.5 2529.56   736.1 2535.35   754.9 2545.11   803.6 2573.41   827.4 2584.84
#Mann= 8 ,-1 , 0
       0     .06       0   15.31      .1       0  114.63     .05       0
  213.95      .1       0  313.27     .05       0   454.7    .045       0
   466.9     .05       0  710.56      .1       0
#XS Ineff= 2 , 0
             435  2513.6     485            2513
Permanent Ineff=
       F       F
Bank Sta=454.7,466.9
XS Rating Curve= 0 ,0
Exp/Cntr(USF)=0,0
Exp/Cntr=0.5,0.3

Type RM Length L Ch R = 1 ,3503    ,91.8,94.2,95.6
XS GIS Cut Line= 2
2415864.48363435598293.2581594362415048.85817748598432.169370058
#Sta/Elev= 30
       0  2565.3      14 2562.94    23.5 2559.81    47.9    2560    72.2 2553.53
  119.192545.995   149.3 2540.71  218.512521.507   250.7 2515.26   299.4  2512.8
   368.4 2513.85   400.9 2511.68  417.152506.691   423.4 2505.25   429.3 2504.62
   436.9 2505.11   499.3 2510.16  516.472510.223   550.5 2510.51   571.3 2519.01
   603.7  2522.5   643.4 2518.43   653.2 2519.22   668.6 2524.49     697  2531.8
   729.5 2537.45   766.3 2555.11   798.5  2572.9  814.432580.252   827.4 2586.47
#Mann= 8 ,-1 , 0
       0     .06       0  119.19     .05       0  218.51      .1       0
  417.15     .05       0   423.4    .045       0   436.9     .05       0
  516.47      .1       0  814.43     .05       0
#XS Ineff= 2 , 0
                          507.65         2510.87
Permanent Ineff=
       F       F
Bank Sta=423.4,436.9
XS Rating Curve= 0 ,0
Exp/Cntr(USF)=0,0
Exp/Cntr=0.5,0.3

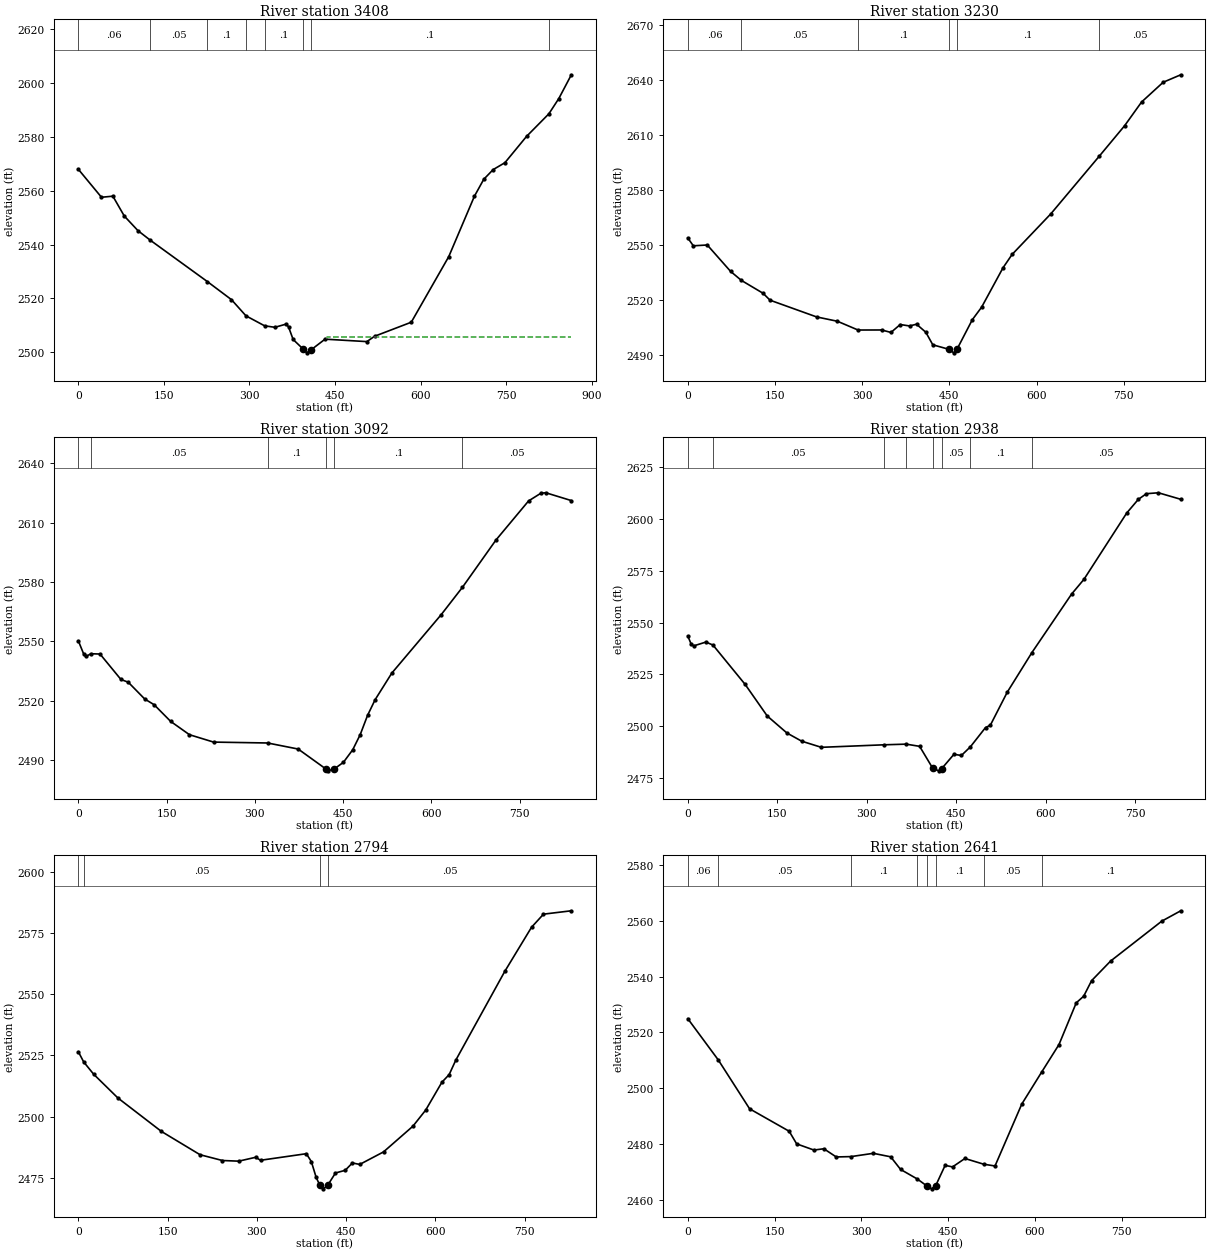
Type RM Length L Ch R = 1 ,3408    ,177.4,178.5,176.7
XS GIS Cut Line= 3
2415865.75348866598265.4763979232415410.19557939598277.067977316
     2415011.825      598368.738
#Sta/Elev= 30
       0 2567.94    40.5 2557.57    60.5 2557.97    80.5  2550.6   104.5 2545.17
  126.042541.632  226.27 2526.25   268.5 2519.54   293.92513.541   326.52509.843
   344.6 2509.28   364.6 2510.49   368.6 2509.41   376.6 2504.76   393.9 2501.26
   400.6  2499.8   408.6    2501   432.6 2504.88   505.9 2503.97   519.4 2505.95
   583.8 2511.17   649.5 2535.52   694.6 2557.99   710.9 2564.24   727.3 2567.83
     748  2570.4   785.9 2580.16  825.062588.549   842.4 2594.18   864.5 2603.05
#Mann= 8 ,-1 , 0
       0     .06       0  126.04     .05       0  226.27      .1       0
   293.9     .05       0   326.5      .1       0   393.9    .045       0
   408.6      .1       0  825.06     .05       0
#XS Ineff= 2 , 0
                           436.1         2505.62
Permanent Ineff=
       F       F
Bank Sta=393.9,408.6
XS Rating Curve= 0 ,0
Exp/Cntr=0.3,0.1

Type RM Length L Ch R = 1 ,3230    ,134.1,138.2,141.8
XS GIS Cut Line= 3
2415810.79824212 598137.232524062415299.21464012598144.858187394
2414971.84272636 598067.28904473
#Sta/Elev= 30
       0 2553.89     9.5 2549.62    33.5 2550.06    73.5 2535.71   92.142530.762
   129.5 2523.73   141.5 2519.96   221.5 2510.85   257.5 2508.46  292.91 2503.69
   333.5 2503.72   349.5 2502.38   365.5 2506.69   381.5 2505.91   393.5 2506.86
   409.5 2502.48   421.5 2495.62   449.62493.152   457.5 2491.25   463.2 2493.25
   489.5 2509.32   505.5 2516.16   542.3 2537.63   557.9  2544.9   624.6 2567.07
  707.46 2598.33   751.4 2615.07   780.7 2628.04   817.8  2638.8   848.1 2642.89
#Mann= 6 ,-1 , 0
       0     .06       0   92.14     .05       0  292.91      .1       0
   449.6    .045       0   463.2      .1       0  707.46     .05       0
Bank Sta=449.6,463.2
XS Rating Curve= 0 ,0
Exp/Cntr=0.3,0.1

Type RM Length L Ch R = 1 ,3092    ,154.2,153.6,152.5
XS GIS Cut Line= 3
     2415822.024      598023.2292415463.00176618598035.659218909
      2415008.31      597886.242
#Sta/Elev= 30
       0 2550.27     8.8 2543.84    12.8 2542.44   21.342543.809    36.8 2543.66
    72.3 2530.82    84.8 2529.41   112.8 2520.93   128.8 2518.05   156.8 2509.65
   188.8 2502.91   229.8 2499.18  321.682498.728   373.6 2495.67   420.7  2485.6
   424.2 2484.66     4352485.641   450.5 2488.97   466.3  2495.3     479 2502.92
   491.5 2512.66   504.3 2520.55   532.8 2534.05   616.7 2563.55  652.882577.403
   709.8 2601.26   765.2 2620.99   786.2  2624.9   794.6 2625.11   837.9 2621.17
#Mann= 6 ,-1 , 0
       0     .06       0   21.34     .05       0  321.68      .1       0
   420.7    .045       0     435      .1       0  652.88     .05       0
Bank Sta=420.7,435
XS Rating Curve= 0 ,0
Exp/Cntr=0.3,0.1

Type RM Length L Ch R = 1 ,2938    ,144,143.8,143
XS GIS Cut Line= 3
     2415830.659      597966.1882415373.53874958597853.443781091
     2415020.145      597812.555
#Sta/Elev= 30
       0 2543.54     5.5 2539.75     9.7 2538.77    30.3 2540.62    42.22539.186
    96.2 2520.16   133.2 2504.92   166.2 2496.71   190.9 2492.76   223.9 2489.79
  328.542490.998  366.042491.324   388.7 2490.27   410.6 2479.72   420.8 2478.43
   425.62479.442   446.3 2486.43   458.7 2485.84  473.852490.033   499.2 2499.33
   507.3 2500.46   535.7 2516.44  577.072535.583   643.5 2563.79   664.3 2570.94
     736 2602.96   755.4 2609.54     769 2612.29   789.1 2612.73   826.6 2609.58
#Mann= 8 ,-1 , 0
       0     .06       0    42.2     .05       0  328.54      .1       0
  366.04     .05       0   410.6    .045       0   425.6     .05       0
  473.85      .1       0  577.07     .05       0
Bank Sta=410.6,425.6
XS Rating Curve= 0 ,0
Exp/Cntr=0.3,0.1

Type RM Length L Ch R = 1 ,2794    ,151.1,153.2,155.1
XS GIS Cut Line= 2
     2415874.518      597806.259     2415059.287      597658.593
#Sta/Elev= 30
       0 2526.47    8.912522.338    25.7 2517.31    66.3 2507.63   139.5 2493.94
   204.5 2484.41     242 2482.05   269.5 2481.78     298 2483.37   306.1 2482.14
   383.1 2484.83   391.5 2481.63   399.6 2475.17   405.6 2472.03   411.8 2470.47
   419.12471.973   432.1 2476.95   448.4 2478.04   460.6 2481.06   472.8 2480.44
   512.8 2485.56   562.2 2496.06   583.7 2502.65     611 2514.05   623.2 2517.18
   634.3 2523.07   716.6 2559.33   761.6 2577.38   781.7 2582.73   828.5 2584.11
#Mann= 4 ,-1 , 0
       0     .06       0    8.91     .05       0   405.6    .045       0
   419.1     .05       0
Bank Sta=405.6,419.1
XS Rating Curve= 0 ,0
Exp/Cntr=0.3,0.1

Type RM Length L Ch R = 1 ,2641    ,136.2,145.9,150.2
XS GIS Cut Line= 3
2415901.17916418597737.5220232122415248.57942651597490.518451979
2415102.02024212597538.232063029
#Sta/Elev= 30
       0 2524.91   52.772510.096   106.8 2492.61   175.2 2484.56   188.1 2480.04
     218 2477.82   235.1 2478.29   256.5 2475.35     2822475.476   320.6 2476.65
   350.6  2475.4   367.7 2470.88  396.612467.444   413.42464.923   421.3 2463.92
   428.32465.011   444.7 2472.34   457.5 2471.78   478.9  2474.8  511.232472.756
   530.9 2472.11   577.2 2494.32   611.5 2505.77   641.4 2515.62   671.3  2530.6
   684.1 2532.96   697.8 2538.54   730.6 2545.56     819 2559.86   851.9 2563.59
#Mann= 8 ,-1 , 0
       0     .06       0   52.77     .05       0     282      .1       0
  396.61     .05       0   413.4    .045       0   428.3      .1       0
  511.23     .05       0   611.5      .1       0
Bank Sta=413.4,428.3
XS Rating Curve= 0 ,0
Exp/Cntr=0.3,0.1

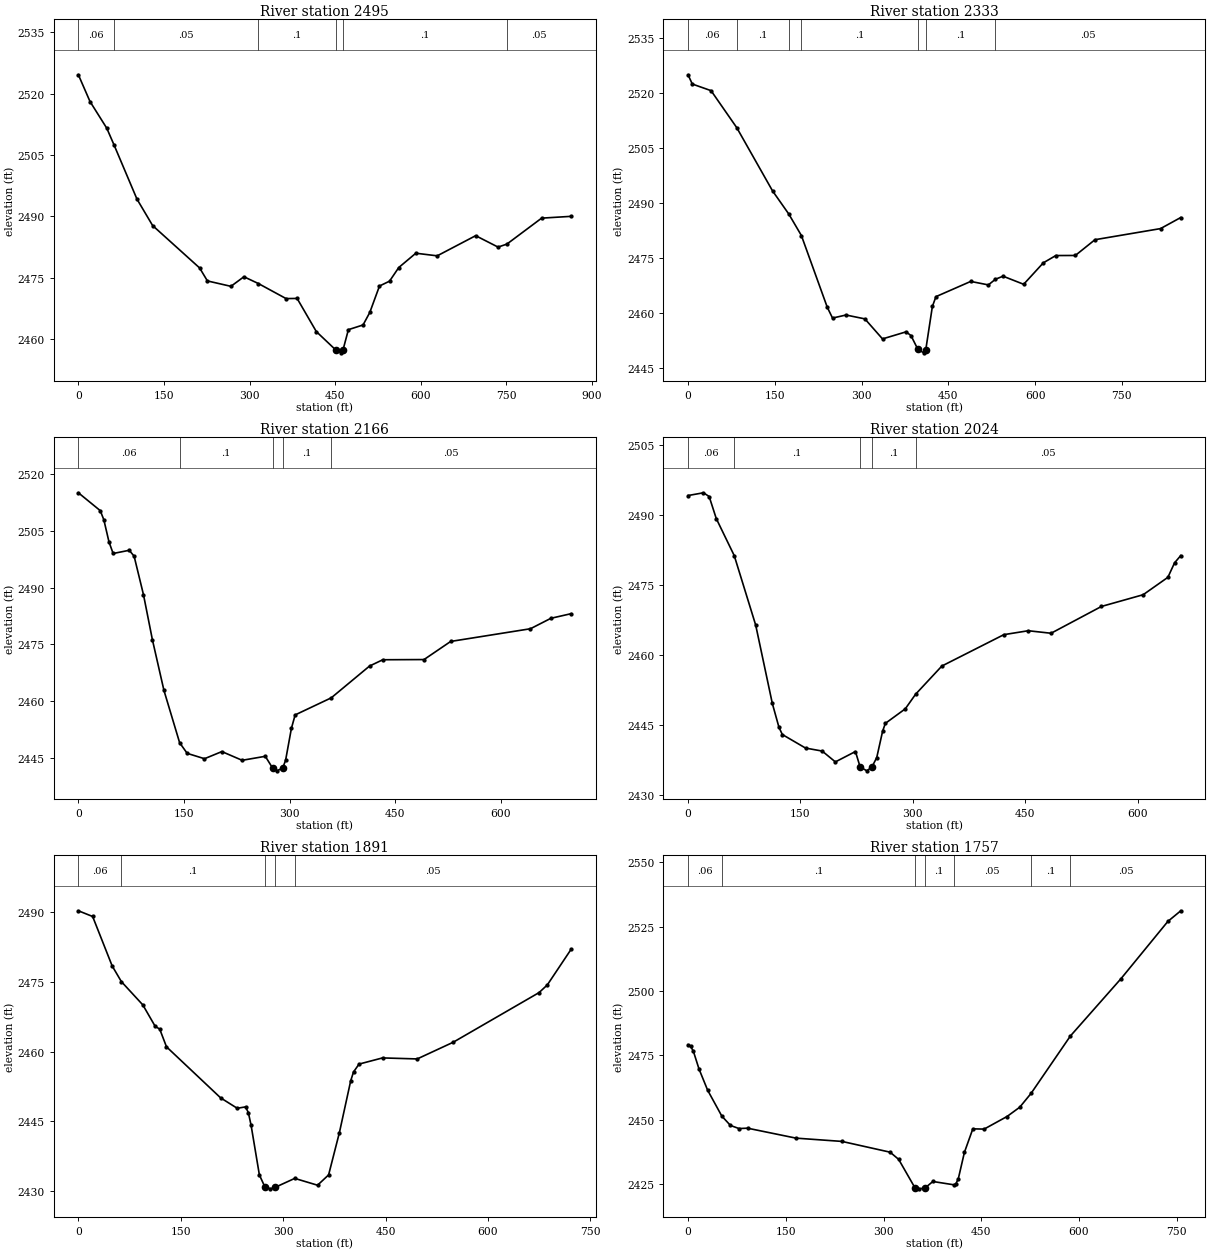
Type RM Length L Ch R = 1 ,2495    ,163.1,162,161.4
XS GIS Cut Line= 3
     2415903.118      597728.0462415618.11952406597569.991961877
     2415318.549      597123.305
#Sta/Elev= 30
       0  2524.6    20.4 2518.06    49.8 2511.53   62.572507.422   102.7 2494.19
   130.2 2487.71   212.5 2477.35   226.2 2474.17   267.4 2472.85   290.2 2475.19
  315.41 2473.54   364.1 2469.85   383.4 2469.89   417.1 2461.78   450.8 2457.33
   460.4 2456.58   463.8 2457.25   473.3 2462.25     499  2463.4   510.8 2466.45
   527.8 2472.93   545.4 2474.11   561.6 2477.45   591.5 2480.95     629 2480.31
   696.4 2485.24   735.6 2482.45  751.072483.176     812 2489.53   863.7 2489.97
#Mann= 6 ,-1 , 0
       0     .06       0   62.57     .05       0  315.41      .1       0
   450.8    .045       0   463.8      .1       0  751.07     .05       0
Bank Sta=450.8,463.8
XS Rating Curve= 0 ,0
Exp/Cntr=0.3,0.1

Type RM Length L Ch R = 1 ,2333    ,176.3,167.1,160.5
XS GIS Cut Line= 3
      2415933.85      597698.7792415561.35903812597223.946139275
     2415350.502      597092.882
#Sta/Elev= 30
       0 2524.91     7.4 2522.39    39.8 2520.59   84.132510.547   146.1 2493.32
  174.16 2487.03  195.952481.182   240.7 2461.66   249.8 2458.72   273.1 2459.55
   305.7  2458.5   336.2 2453.05   376.9 2454.97   385.4 2453.96   397.2 2450.25
   407.4 2449.26     411 2450.11   422.4 2461.88   428.6 2464.55   488.7 2468.69
   519.2 2467.74   531.42469.284   544.6 2470.11   580.2 2467.91   614.2 2473.75
   635.8 2475.73   669.5 2475.75   703.5 2480.04   816.8 2483.06   851.8 2486.08
#Mann= 7 ,-1 , 0
       0     .06       0   84.13      .1       0  174.16     .05       0
  195.95      .1       0   397.2    .045       0     411      .1       0
   531.4     .05       0
Bank Sta=397.2,411
XS Rating Curve= 0 ,0
Exp/Cntr=0.3,0.1

Type RM Length L Ch R = 1 ,2166    ,140.2,142.2,145
XS GIS Cut Line= 3
2416019.51987394597303.6306401222415595.96495188597201.534585395
     2415373.191      597059.189
#Sta/Elev= 30
       0 2515.13    31.1  2510.4    36.2 2507.97    43.5 2502.12    49.4 2499.05
    72.3  2499.9    79.2 2498.34    92.5 2488.15   105.2  2476.2   121.6 2462.78
  143.882448.935   154.6 2446.12   179.2  2444.7   203.9 2446.59   232.7 2444.28
   265.6 2445.34     276 2442.22   282.1 2441.49   290.3 2442.24   294.4 2444.26
   302.7 2452.75     308  2456.3  359.292460.822   413.7 2469.24   432.5 2470.91
   491.1 2470.96     529 2475.76   642.3 2479.12   671.4 2481.89   700.1 2483.11
#Mann= 5 ,-1 , 0
       0     .06       0  143.88      .1       0     276    .045       0
   290.3      .1       0  359.29     .05       0
#XS Ineff= 2 , 0
          204.41  2446.5
Permanent Ineff=
       F       F
Bank Sta=276,290.3
XS Rating Curve= 0 ,0
Exp/Cntr=0.3,0.1

Type RM Length L Ch R = 1 ,2024    ,136.5,133,129.6
XS GIS Cut Line= 2
2416022.66840177597215.1819262252415429.85346103596930.811968485
#Sta/Elev= 30
       0 2494.09    20.6 2494.68    28.2 2493.88    37.7 2489.16   61.672481.242
    90.3 2466.38   112.5 2449.62   121.3 2444.55   125.8 2442.99   156.8 2440.09
     179 2439.45   196.6 2437.13   223.4 2439.35   229.6 2436.06   238.6 2435.22
   245.5 2436.08   251.8 2438.05   259.6 2443.67   263.3 2445.37   289.9 2448.48
  303.682451.605   338.7 2457.63   421.4 2464.34     454 2465.18   484.4 2464.64
   551.6 2470.37   607.3 2472.88   640.3  2476.6   649.2  2479.7   657.5 2481.26
#Mann= 5 ,-1 , 0
       0     .06       0   61.67      .1       0   229.6    .045       0
   245.5      .1       0  303.68     .05       0
Bank Sta=229.6,245.5
XS Rating Curve= 0 ,0
Exp/Cntr=0.3,0.1

Type RM Length L Ch R = 1 ,1891    ,131.4,133.6,137.4
XS GIS Cut Line= 3
2416070.39416249597166.3716567262415955.65233667 597010.17746103
     2415434.938      596922.174
#Sta/Elev= 30
       0 2490.33    20.9  2489.1    49.5 2478.46      632475.079    94.4 2470.07
   112.5 2465.46   119.2 2464.85   129.1 2461.04   208.4 2450.05   232.7 2447.81
   244.9  2448.1     249 2446.89     253 2444.19   265.2 2433.45   273.22430.891
   281.4 2430.46   288.22430.776  316.98 2432.71   350.4 2431.24   366.6 2433.46
   382.4 2442.55     399 2453.73   403.1 2455.62   411.2 2457.32   445.6 2458.65
   496.4 2458.43   549.1 2462.02   674.9 2472.71     687 2474.36   721.9 2482.04
#Mann= 5 ,-1 , 0
       0     .06       0      63      .1       0   273.2    .045       0
   288.2      .1       0  316.98     .05       0
Bank Sta=273.2,288.2
XS Rating Curve= 0 ,0
Exp/Cntr=0.3,0.1

Type RM Length L Ch R = 1 ,1757    ,197.2,198.6,201.8
XS GIS Cut Line= 2
2416184.72361407597018.5129792582415493.59253897596711.923679939
#Sta/Elev= 30
       0 2479.15     3.8 2478.61     8.2 2476.64    16.9 2469.73    30.1 2461.53
   51.862451.496    65.1 2447.87    78.2 2446.67    91.3 2446.81   165.7 2442.95
   236.2 2441.68   310.1  2437.5   323.2 2434.72   348.3 2423.65   353.9 2423.29
   363.5 2423.59   375.7 2426.14  407.662424.865   410.7 2425.05   414.8 2427.28
   424.1 2437.43     437 2446.55   454.4 2446.46   489.5 2451.34     509 2454.94
  526.262460.261  586.772482.572   664.5 2504.82   736.3 2526.99   756.1 2531.11
#Mann= 7 ,-1 , 0
       0     .06       0   51.86      .1       0   348.3    .045       0
   363.5      .1       0  407.66     .05       0  526.26      .1       0
  586.77     .05       0
Bank Sta=348.3,363.5
XS Rating Curve= 0 ,0
Exp/Cntr=0.3,0.1

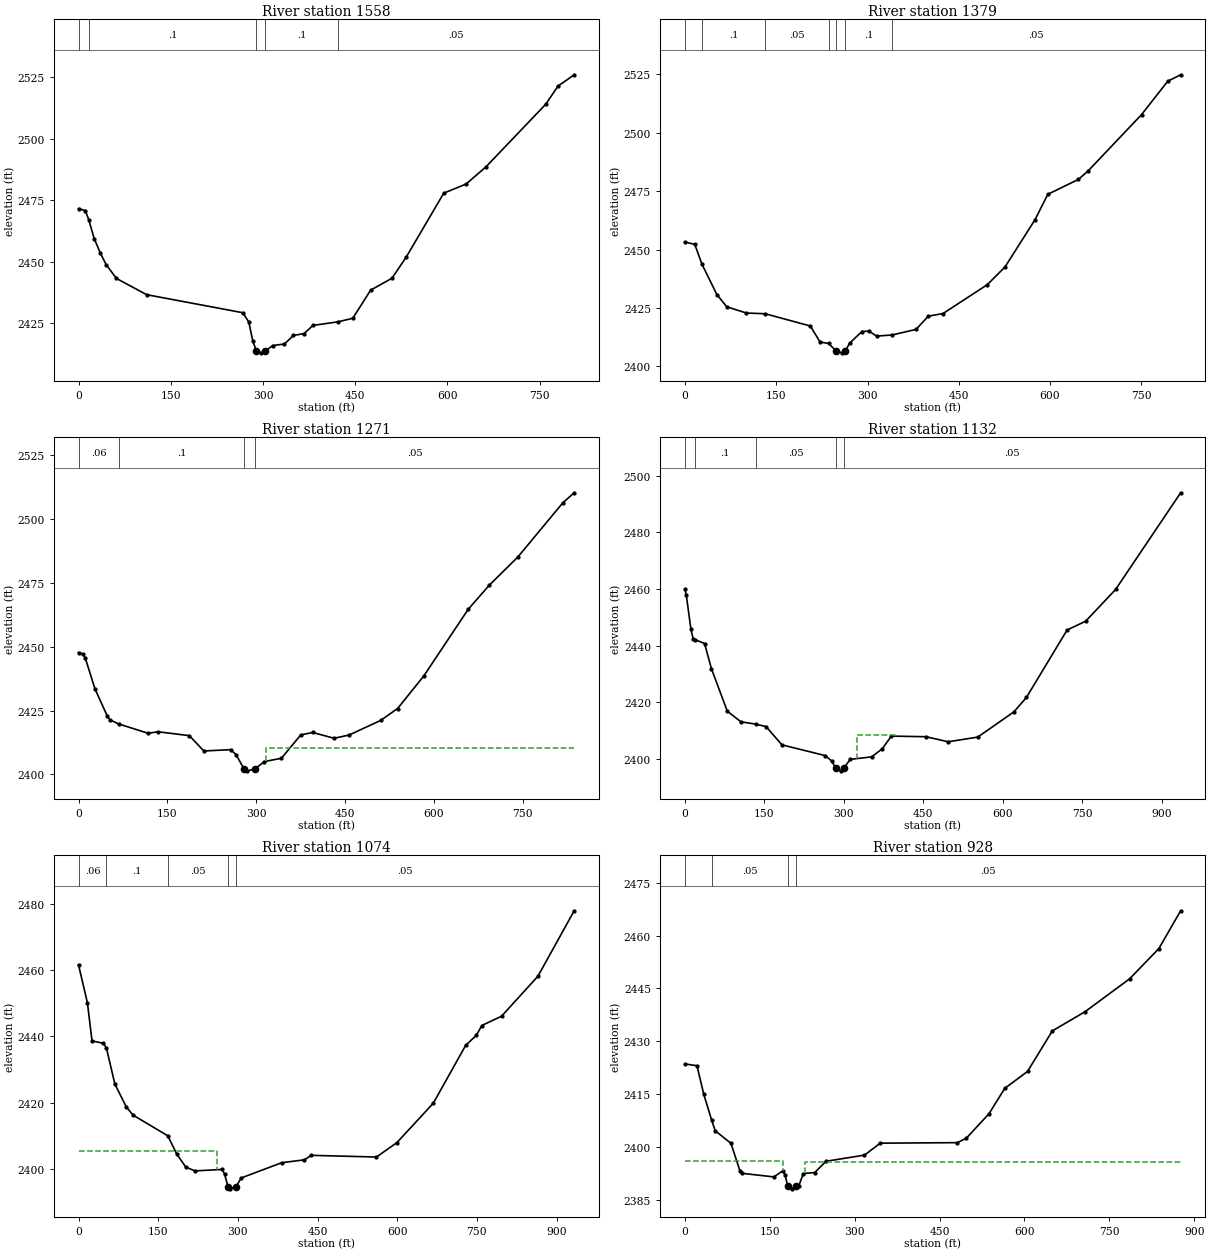
Type RM Length L Ch R = 1 ,1558    ,185.6,179.4,174.7
XS GIS Cut Line= 3
2416230.35080977596898.9382595022415808.69258747596612.588272718
2415515.34990546596655.240696544
#Sta/Elev= 30
       0 2471.55      11 2470.73    16.52467.109    25.5 2459.36    35.2 2453.63
    44.9 2448.76    61.7 2443.13   110.7 2436.53   267.3 2429.18   276.9  2425.4
   283.4 2417.77   289.2 2413.65   296.3 2412.86   303.6 2413.47   315.6 2415.82
   334.9 2416.46   349.6 2419.92   366.9 2420.71   381.3 2424.02  421.422425.447
   446.1 2426.92   475.1 2438.38   509.7 2443.19   533.4 2451.99     594 2477.83
   630.4 2481.55   662.5  2488.5   759.7 2513.97   779.9  2521.4   806.1 2525.99
#Mann= 5 ,-1 , 0
       0     .06       0    16.5      .1       0   289.2    .045       0
   303.6      .1       0  421.42     .05       0
Bank Sta=289.2,303.6
XS Rating Curve= 0 ,0
Exp/Cntr=0.3,0.1

Type RM Length L Ch R = 1 ,1379    ,108.7,108.5,111.3
XS GIS Cut Line= 3
2416301.15163067596600.0014601122415780.37225911596526.053936052
2415505.03573335596612.588272718
#Sta/Elev= 30
       0 2453.24    16.1 2452.28   27.972443.752    52.4 2430.81    68.6 2425.56
   100.9 2422.88  131.992422.569     206 2417.33   222.1 2410.46  236.012409.866
     249  2406.5   258.5 2405.84   263.2 2406.47   270.6 2409.98   290.8 2414.96
   302.1 2415.15     315 2413.01  340.032413.476   379.7 2415.86   399.9 2421.52
   424.1 2422.67   496.8 2435.01     526 2442.62   575.4 2462.89   596.3  2473.7
   646.6 2480.08   662.7 2483.75   750.4 2507.83   793.5 2522.13   814.6 2524.87
#Mann= 7 ,-1 , 0
       0     .06       0   27.97      .1       0  131.99     .05       0
  236.01      .1       0     249    .045       0   263.2      .1       0
  340.03     .05       0
Bank Sta=249,263.2
XS Rating Curve= 0 ,0
Exp/Cntr(USF)=0,0
Exp/Cntr=0.3,0.1

Type RM Length L Ch R = 1 ,1271    ,136.7,138.4,141.2
XS GIS Cut Line= 3
2416324.36664512596513.8950400562415797.60853756596403.445759439
2415527.14940169596529.471220656
#Sta/Elev= 30
       0 2447.71     7.3 2447.19    11.4 2445.58    27.7 2433.52    48.2 2423.04
    52.9 2421.39   67.942419.724   117.6 2416.09   134.2 2416.69   187.1 2415.16
   211.6 2409.15   256.6 2409.68   265.8 2407.76   279.3 2402.16   285.2 2401.38
   297.4 2402.08   313.8 2405.02   342.4  2406.3   375.1 2415.45   395.5  2416.4
   431.3 2414.14   456.8 2415.41   509.9 2421.12   538.6 2425.79   582.8 2438.55
   657.7 2464.63     693 2474.01   741.6 2485.15   817.6  2506.4   836.6 2510.29
#Mann= 4 ,-1 , 0
       0     .06       0   67.94      .1       0   279.3    .045       0
   297.4     .05       0
#XS Ineff= 2 , 0
                          315.81          2410.5
Permanent Ineff=
       F       F
Bank Sta=279.3,297.4
XS Rating Curve= 0 ,0
Exp/Cntr(USF)=0,0
Exp/Cntr=0.5,0.3

Type RM Length L Ch R = 1 ,1132    ,57.5,57.8,57.5
XS GIS Cut Line= 3
2416363.61368824596432.911522769 2415839.0704176596226.726834948
2415542.36501757596451.462717783
#Sta/Elev= 30
       0 2459.86     2.6 2457.72    11.2 2445.79    15.5 2442.41   18.362442.148
      37 2440.74    49.8 2431.88    79.9 2416.83   105.6 2413.07  133.832412.247
     153 2411.38   183.1 2404.92   264.7 2401.13   277.6 2399.14   284.5 2396.59
   293.8 2395.74     300 2396.75     312 2399.79   352.4 2400.68   372.2 2403.47
   389.6 2408.02   455.2  2407.8   496.8 2406.01   552.7 2407.66   621.1 2416.59
   644.6 2421.66   721.4  2445.5   756.5 2448.63     813 2459.83   935.8 2494.01
#Mann= 5 ,-1 , 0
       0     .06       0   18.36      .1       0  133.83     .05       0
   284.5    .045       0     300     .05       0
#XS Ineff= 3 ,-1
       0     255  2400.5  324.99  396.92 2408.29  396.92   935.8  2400.5
Permanent Ineff=
       F       F       F
Bank Sta=284.5,300
XS Rating Curve= 0 ,0
Exp/Cntr(USF)=0,0
Exp/Cntr=0.5,0.3

Type RM Length L Ch R = 1 ,1074    ,150.8,146.2,141.1
XS GIS Cut Line= 3
2416384.85393451596380.5189152962415863.14269671596174.334227476
2415566.43729668596399.070110311
#Sta/Elev= 30
       0 2461.56    16.8 2450.08    25.4 2438.65    46.9 2437.91   52.542436.527
    68.4 2425.67    89.9 2418.78   102.8 2416.28  168.142410.061   184.5 2404.71
   201.7 2400.69   218.9 2399.49   270.6 2399.93   274.9 2398.57   281.9 2394.54
     285 2394.09   296.4 2394.73   306.5 2397.38   382.4 2401.95   425.4 2402.83
   438.3 2404.18     561 2403.67   599.5 2408.02     668 2419.88   728.9 2437.29
     749 2440.34   759.3 2443.28   796.5 2446.08     865 2458.13   933.2 2477.83
#Mann= 5 ,-1 , 0
       0     .06       0   52.54      .1       0  168.14     .05       0
   281.9    .045       0   296.4     .05       0
#XS Ineff= 2 , 0
          261.52 2405.63
Permanent Ineff=
       F       F
Bank Sta=281.9,296.4
XS Rating Curve= 0 ,0
Exp/Cntr(USF)=0,0
Exp/Cntr=0.5,0.3

Type RM Length L Ch R = 1 ,928     ,199.2,201.1,202
XS GIS Cut Line= 3
2416346.39487412596133.8847384012415770.86617701596141.878192527
 2415568.5491726596363.927510068
#Sta/Elev= 30
       0 2423.52    21.2 2423.02    33.2 2414.91   47.162407.547    53.4 2404.54
    81.2 2400.98    97.2 2393.12   101.2 2392.44   157.2 2391.43   173.2  2393.2
   177.2 2391.83   181.32388.958   189.2 2388.04   196.32388.857   201.2 2388.92
   209.2 2392.39   229.2 2392.66   249.2 2395.87   317.2 2397.62   345.2 2401.02
   481.2 2401.16   497.2 2402.41   537.2 2409.36   565.2 2416.59   605.4 2421.39
   649.2  2432.9   707.3 2438.39   785.8 2447.71   837.5 2456.29     876 2467.04
#Mann= 4 ,-1 , 0
       0     .06       0   47.16     .05       0   181.3    .045       0
   196.3     .05       0
#XS Ineff= 2 , 0
          173.52 2395.88   212.7          2395.7
Permanent Ineff=
       F       F
Bank Sta=181.3,196.3
XS Rating Curve= 0 ,0
Exp/Cntr(USF)=0,0
Exp/Cntr=0.3,0.1