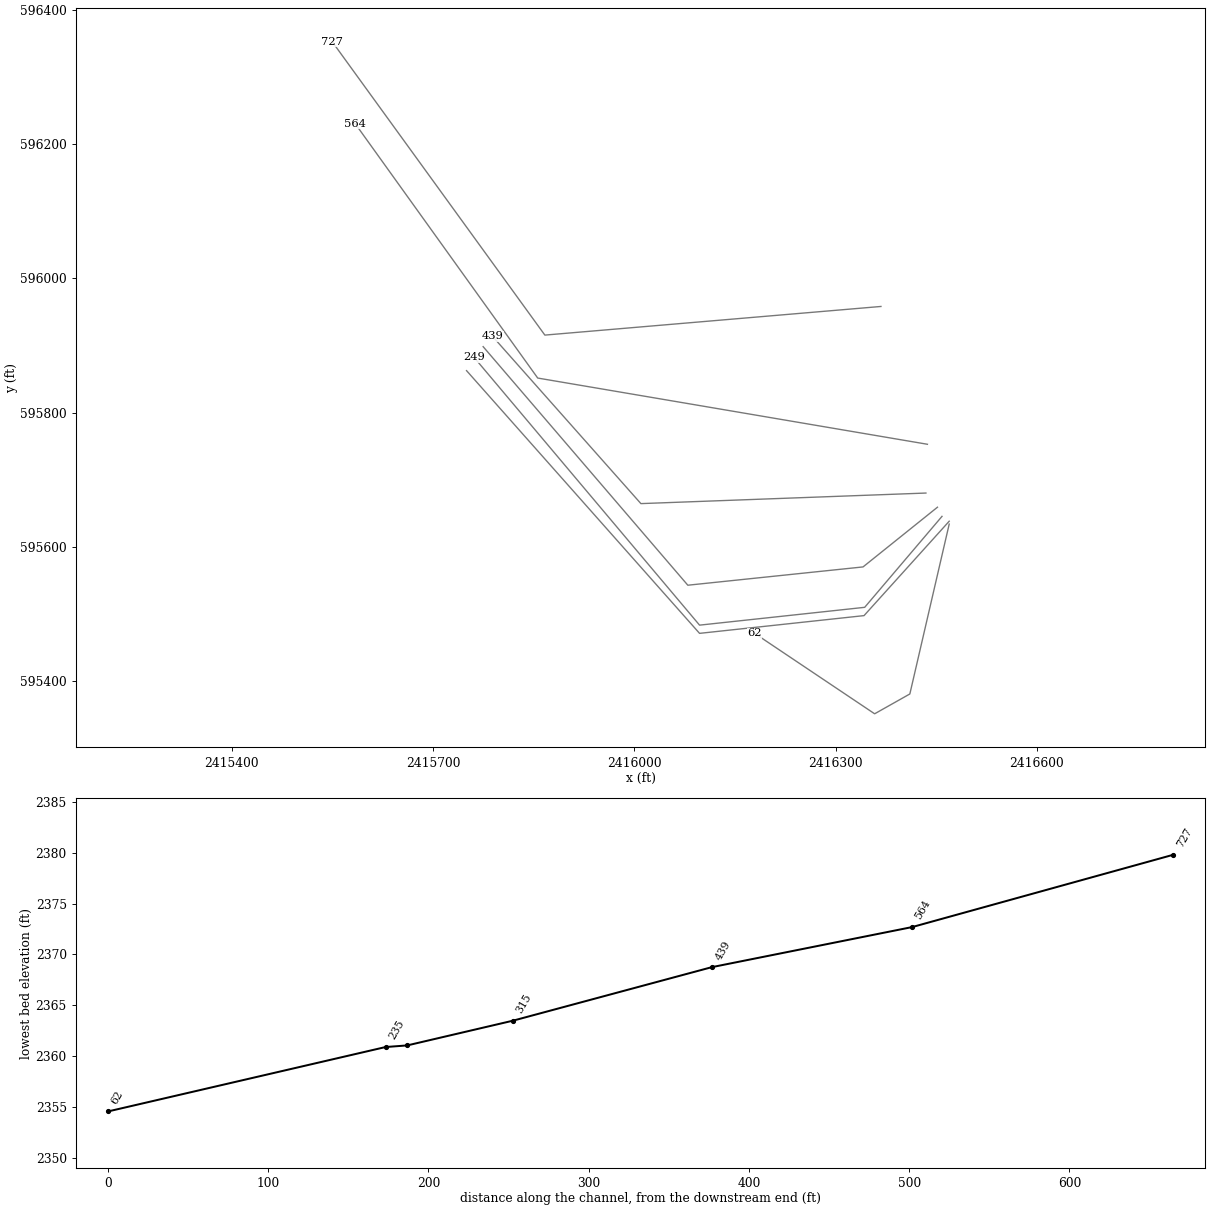
HEC-RAS study GRAVLCKRN.prj: GRAVLCKRN

--- GRAVLCKRN.g01 (geometry) --- (continued)

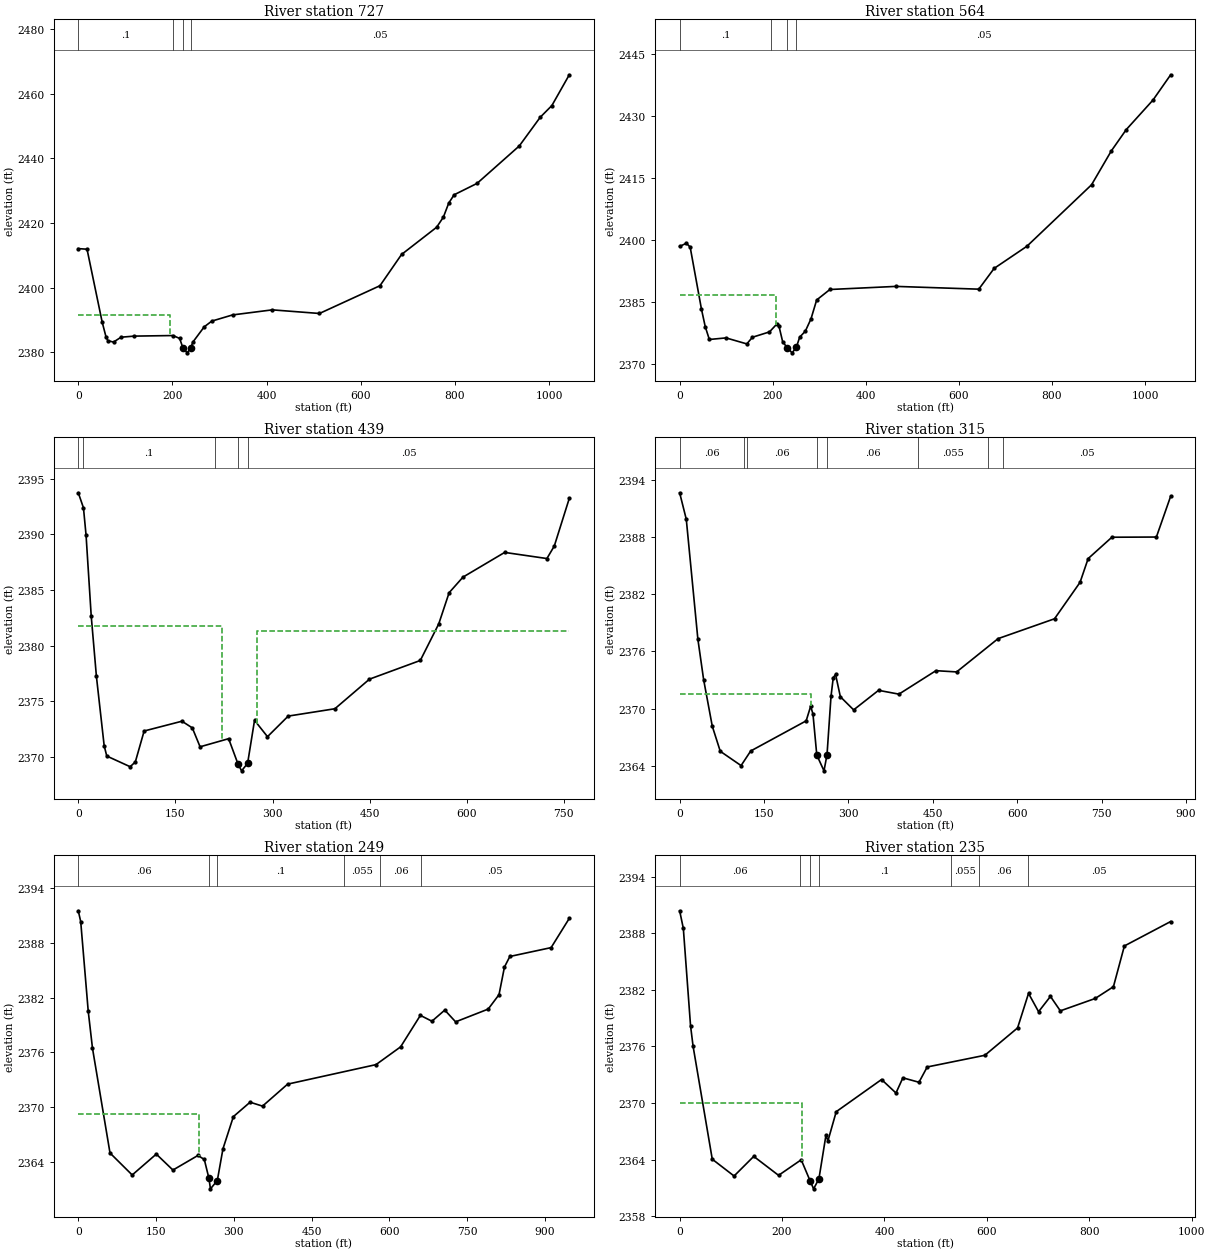
Type RM Length L Ch R = 1 ,727     ,167.9,163.1,159.5
XS GIS Cut Line= 3
 2416367.7107518595958.0287476162415866.78762653595915.396992274
2415549.71394617596352.372484527
#Sta/Elev= 30
       0 2412.09    18.6  2411.9    50.7 2389.35    58.7 2384.85    62.7 2383.59
    74.8 2383.14    90.8 2384.65   118.9 2384.99   201.22385.168   215.2 2384.27
  222.26 2381.34   231.3 2379.81   238.7 2381.34   243.3 2383.14   267.4 2387.86
   283.5 2389.64   327.6 2391.55   411.9 2393.12   512.1    2392   640.6  2400.6
   686.4 2410.27   760.9  2418.7   775.2 2421.83   786.6 2426.18     798 2428.75
   846.8 2432.29   936.4 2443.88   980.9 2452.77  1005.6 2456.39  1042.6 2465.92
#Mann= 4 ,-1 , 0
       0      .1       0   201.2     .05       0  222.26    .045       0
   238.7     .05       0
#XS Ineff= 2 , 0
          195.57 2391.63
Permanent Ineff=
       F       F
Bank Sta=222.26,238.7
XS Rating Curve= 0 ,0
Exp/Cntr(USF)=0,0
Exp/Cntr=0.3,0.1

Type RM Length L Ch R = 1 ,564     ,122.3,124.9,127.5
XS GIS Cut Line= 3
2416436.98735423595752.8634250332415856.12968769595851.449359261
2415584.35224739 596229.80618792
#Sta/Elev= 30
       0 2398.41    14.4 2399.18    22.6 2398.25    46.9 2383.23      55 2379.01
    63.8 2375.92    99.6  2376.3   144.3 2374.85   156.4 2376.46     193 2377.75
   209.2  2379.7   213.2 2379.25   221.4 2375.34     2312373.969   241.6 2372.69
   250.62373.985   257.9 2376.48     270 2377.92   282.2  2380.9   294.4 2385.47
   322.8    2388   464.8 2388.75   642.7 2388.08   675.7  2393.1   746.1 2398.45
     885 2413.31   927.5  2421.5   959.5 2426.64    1017 2433.79    1055  2439.9
#Mann= 4 ,-1 , 0
       0      .1       0  197.07     .05       0     231    .045       0
   250.6     .05       0
#XS Ineff= 2 , 0
          207.55 2386.57
Permanent Ineff=
       F       F
Bank Sta=231,250.6
XS Rating Curve= 0 ,0
Exp/Cntr(USF)=0,0
Exp/Cntr=0.3,0.1

Type RM Length L Ch R = 1 ,439     ,124.5,124.2,124.7
XS GIS Cut Line= 3
2416434.74599899595680.2459668072416009.94107354 595664.51245105
2415788.65145297595913.681578552
#Sta/Elev= 30
       0 2393.74       8 2392.39      12 2389.94      20 2382.65      28 2377.24
      40    2371      44 2370.08    80.1 2369.12    88.1 2369.55   101.7 2372.33
   160.1 2373.21   176.1 2372.61   188.1 2370.91   232.2 2371.64   246.52369.389
   252.2 2368.75   261.52369.424   272.2 2373.29   292.2 2371.82   324.2 2373.67
   396.3 2374.33   449.7 2376.99   528.2 2378.67   556.7 2381.96   572.7 2384.76
   594.1 2386.16   658.5 2388.38   723.7 2387.83   735.1 2388.95   758.3 2393.24
#Mann= 5 ,-1 , 0
       0     .06       0       8      .1       0  210.58     .05       0
   246.5    .045       0   261.5     .05       0
#XS Ineff= 2 , 0
          222.12  2381.8  276.21         2381.36
Permanent Ineff=
       F       F
Bank Sta=246.5,261.5
XS Rating Curve= 0 ,0
Exp/Cntr(USF)=0,0
Exp/Cntr=0.5,0.3

Type RM Length L Ch R = 1 ,315     ,64.9,65.9,65.9
XS GIS Cut Line= 4
2416451.95899895595659.1732794892416341.01063679595570.264839352
2416079.86193907595543.0320568292415774.81553929595898.181042835
#Sta/Elev= 30
       0 2392.63    11.8 2389.85    32.4 2377.28    42.6 2373.05      58 2368.16
    72.2 2365.53   109.2 2364.03   126.3 2365.56   224.9 2368.72   232.9 2370.25
     237 2369.44   243.82365.133   256.6 2363.48     262 2365.18   269.1 2371.31
   273.1 2373.26   277.2 2373.58   285.7 2371.25   309.3 2369.87   353.6 2371.92
   389.8 2371.52   455.6 2373.98   492.4 2373.85   566.1 2377.34   666.4 2379.42
   711.8 2383.24   726.2 2385.73   768.4 2387.97   847.5 2387.99   872.9 2392.27
#Mann= 8 ,-1 , 0
       0     .06       0  114.86      .1       0  120.33     .06       0
   243.8    .045       0     262     .06       0  423.67    .055       0
  547.81     .06       0  575.39     .05       0
#XS Ineff= 2 , 0
          232.83 2371.49  279.19         2370.41
Permanent Ineff=
       F       F
Bank Sta=243.8,262
XS Rating Curve= 0 ,0
Exp/Cntr(USF)=0,0
Exp/Cntr=0.5,0.3

Type RM Length L Ch R = 1 ,249     ,13.4,13.5,13
XS GIS Cut Line= 4
2416458.70648407595645.5348025832416343.46444229595510.111499886
2416097.34362325595483.594330634 2415761.0160344 595882.53698134
#Sta/Elev= 30
       0 2391.54     4.7 2390.35    19.2 2380.52    27.4 2376.47    61.2 2364.98
     104 2362.57   150.5 2364.86   182.6 2363.11   230.8 2364.71   243.1 2364.27
   251.92362.233     255 2361.05   268.22361.959   279.1 2365.44   299.2 2368.97
   331.4 2370.55   355.4 2370.12   403.8 2372.53   574.3 2374.67   621.8 2376.62
   659.9 2380.07   682.2 2379.43     707 2380.65   727.9 2379.36   790.7 2380.76
   811.6 2382.34   822.1 2385.37   832.5 2386.53   912.1  2387.5   947.2 2390.71
#Mann= 6 ,-1 , 0
       0     .06       0   251.9    .045       0   268.2      .1       0
  511.85    .055       0  582.95     .06       0  661.25     .05       0
#XS Ineff= 2 , 0
          233.54 2369.29  326.04         2370.16
Permanent Ineff=
       F       F
Bank Sta=251.9,268.2
XS Rating Curve= 0 ,0
Exp/Cntr(USF)=0,0
Exp/Cntr=0.5,0.3

Type RM Length L Ch R = 1 ,235     ,168.1,173.3,178.4
XS GIS Cut Line= 4
2416469.44068312595638.3069165512416342.50651211595497.768307688
2416097.34362325595471.3571517122415750.06761822 595862.47950515
#Sta/Elev= 30
       0 2390.37     7.2  2388.5    21.3 2378.17    26.2 2376.02    63.7 2364.03
   106.3 2362.25   144.7 2364.33   193.2 2362.32   237.4 2363.97   255.1  2361.7
   261.6 2360.89     2722361.945   285.7 2366.56   289.7 2365.99   305.8 2369.07
   394.3 2372.48   422.5 2371.05     436 2372.66   467.4 2372.19   483.5 2373.81
   596.1 2375.05     660 2377.95   681.4 2381.61     701 2379.67   724.2 2381.29
   743.5 2379.76   811.5 2381.07   847.2 2382.32   868.6 2386.64     959 2389.23
#Mann= 7 ,-1 , 0
       0     .06       0  234.92      .1       0   255.1    .045       0
     272      .1       0  530.38    .055       0  585.52     .06       0
  679.77     .05       0
#XS Ineff= 2 , 0
           238.1    2370
Permanent Ineff=
       F       F
Bank Sta=255.1,272
XS Rating Curve= 0 ,0
Exp/Cntr(USF)=0,0
Exp/Cntr=0.3,0.1

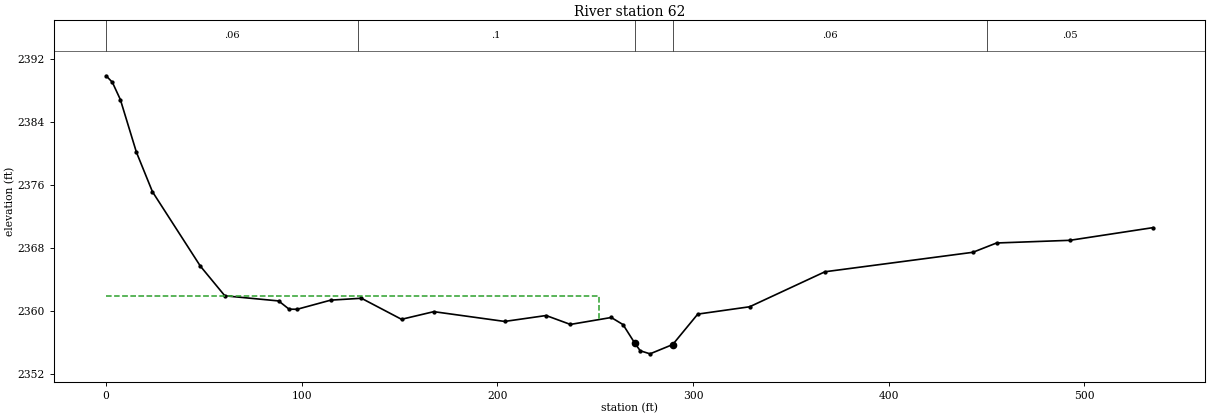
Type RM Length L Ch R = 1 ,62      ,,,
XS GIS Cut Line= 4
 2416469.4497178595634.0137902962416410.78467412595381.133951391
2416358.30396046595351.6054853192416179.44858902595471.371237818
#Sta/Elev= 30
       0 2389.82     3.2    2389     7.3  2386.8    15.5 2380.13    23.7 2375.11
    48.2 2365.67    60.7 2361.91    88.2 2361.26    93.5 2360.22    97.6  2360.2
   114.8 2361.36   130.5  2361.6     151 2358.93   167.5  2359.9   203.7 2358.66
   224.9 2359.41   237.3 2358.28   258.2 2359.16   264.2 2358.26   270.1 2355.95
     273 2354.94     278 2354.55   289.6 2355.73   302.4 2359.59   328.9 2360.52
   367.4 2364.96     443 2367.43   455.1 2368.61   492.6 2368.95   535.1 2370.56
#Mann= 5 ,-1 , 0
       0     .06       0   128.6      .1       0   270.1    .045       0
   289.6     .06       0   450.2     .05       0
#XS Ineff= 2 , 0
          251.98 2361.94
Permanent Ineff=
       F       F
Bank Sta=270.1,289.6
XS Rating Curve= 0 ,0
Exp/Cntr(USF)=0,0
Exp/Cntr=0.3,0.1
LCMann Table=0

Chan Stop Cuts=-1
Use User Specified Reach Order=0
Composite Channel Slope=5